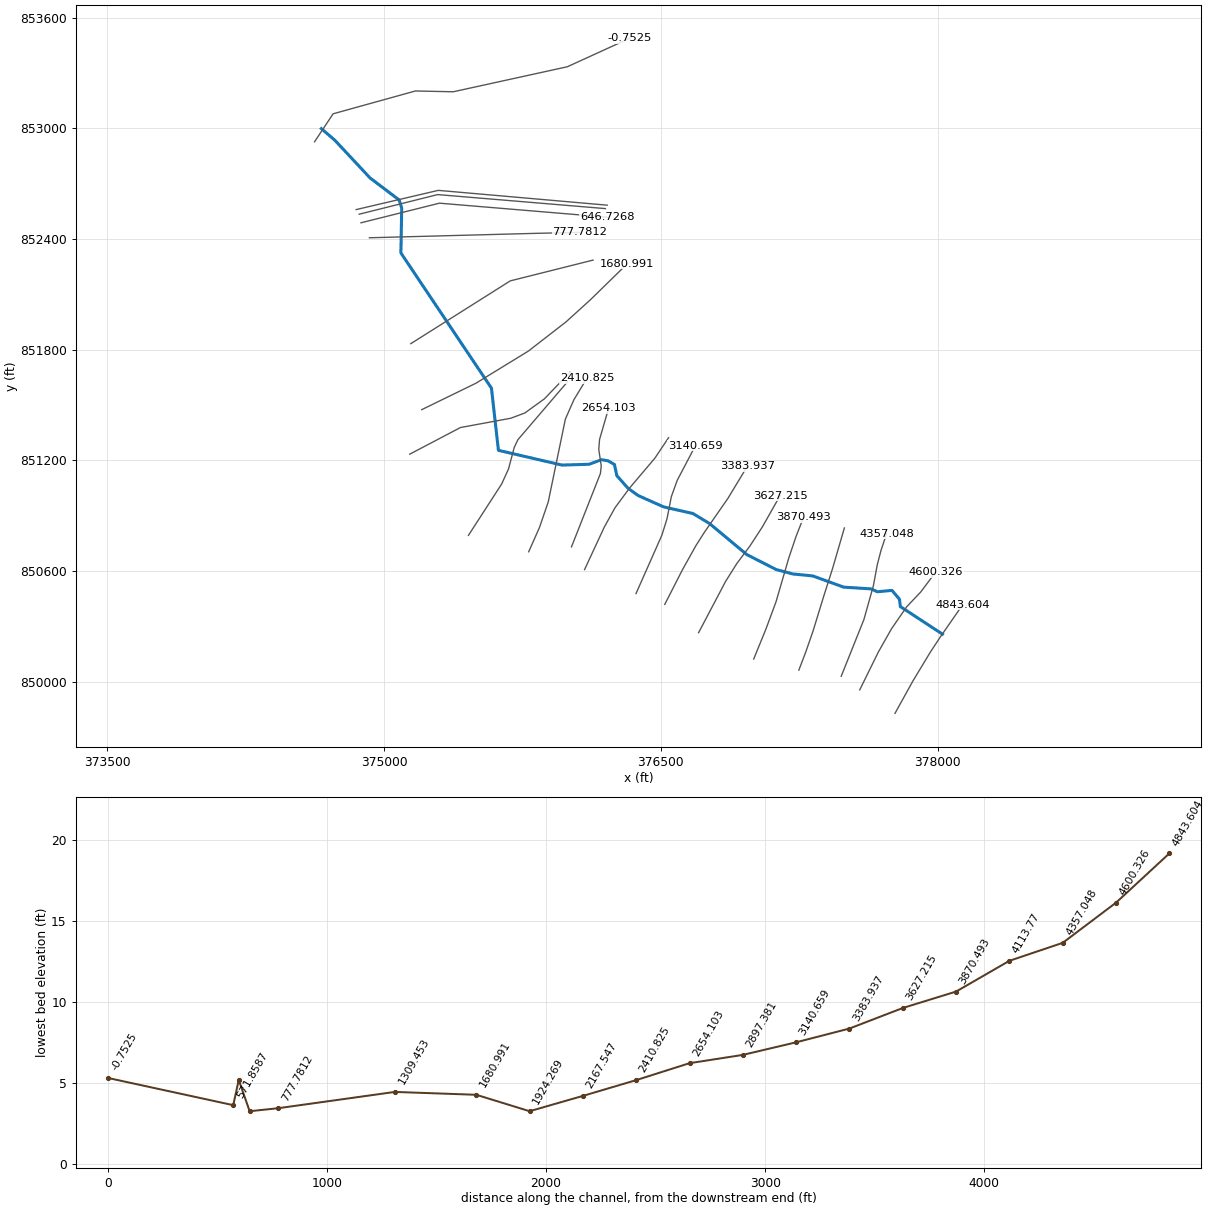
--- 6632_ras.prj (project) ---

Proj Title=6632
Current Plan=p01
Default Exp/Contr=0.3,0.1
English Units
Geom File=g01
Flow File=f01
Plan File=p01
Y Axis Title=Elevation
X Axis Title(PF)=Main Channel Distance
X Axis Title(XS)=Station
BEGIN DESCRIPTION:
RFD model 6632 exported to HEC-RAS
END DESCRIPTION:

--- 6632_ras.p01 (plan) ---

Plan Title=Plan 01
Program Version=4.10
Short Identifier=Plan 01
Geom File=g01
Flow File=f01
Subcritical Flow
Calc Critical at every XS
Secant Critical Depth

--- 6632_ras.f01 (steady flow) ---

Flow Title=Flow 01
Program Version=5.01
Number of Profiles= 6
Profile Names=10yr,25yr,50yr,100yr,100plus,500yr
River Rch & RM=6632,20,4843.604
  108.38  188.64  268.94  349.98  510.97 1032.31
River Rch & RM=6632,20,2410.825
  115.78  201.62  287.55  374.27  546.43 1093.99
River Rch & RM=6632,20,2167.547
  123.07   214.4  305.89  398.22   581.4 1154.33
River Rch & RM=6632,20,1924.269
  126.49  220.43  314.55  409.56  597.96 1182.85
River Rch & RM=6632,20,1680.991
  132.42  230.87  329.57  429.23  626.68 1232.13
River Rch & RM=6632,20,1309.453
     143  249.52  356.41  464.38  677.99  1319.4
River Rch & RM=6632,20,777.7812
  198.71  347.97  498.35  650.56  949.82 1769.31
River Rch & RM=6632,20,646.7268
  199.98  350.23   501.6  654.83  956.05  1779.4
River Rch & RM=6632,20, -0.7525
  207.49  363.56  520.88  680.18  993.07 1839.45
Boundary for River Rch & Prof#=6632,20,1
Up Type= 0
Dn Type= 2
Boundary for River Rch & Prof#=6632,20,2
Up Type= 0
Dn Type= 2
Boundary for River Rch & Prof#=6632,20,2
Up Type= 0
Dn Type= 2
Boundary for River Rch & Prof#=6632,20,2
Up Type= 0
Dn Type= 2
Boundary for River Rch & Prof#=6632,20,2
Up Type= 0
Dn Type= 2
Boundary for River Rch & Prof#=6632,20,2
Up Type= 0
Dn Type= 2

--- 6632_ras.g01 (geometry) ---

Geom Title=6632
Program Version=4.10

River Reach=6632,20
Reach XY= 30
378026.882647634850257.746519163377798.426598787850407.421963289
377793.739098787850447.005296603377753.114098758850494.921963319
377673.947432131850487.630296633377639.051598758850503.255296633
377491.655765563850512.630296618377323.082804769850573.560524032
377216.655765444 850583.98446326377125.509932101850607.942796618
376966.134932101850689.192796588376764.127553761850857.508768842
376674.066789746850911.762241066 376515.64665097850947.569532707
376376.757761985851009.418491051376321.419220328851049.566060483
376261.740400851851116.840366066376248.719567567851177.604254976
376215.082414746851197.135504931376179.275123239851203.645921618
376110.915748119851178.689324379375964.431373119851174.349046618
 375619.73844716851254.323090747375582.008892149 851591.10081242
375091.064830065852324.282467902375095.473039746852566.724625319
375081.849924028 852611.32373479374923.945262045 852730.61351417
374734.061870158852934.175207511374659.862168044852998.331924722

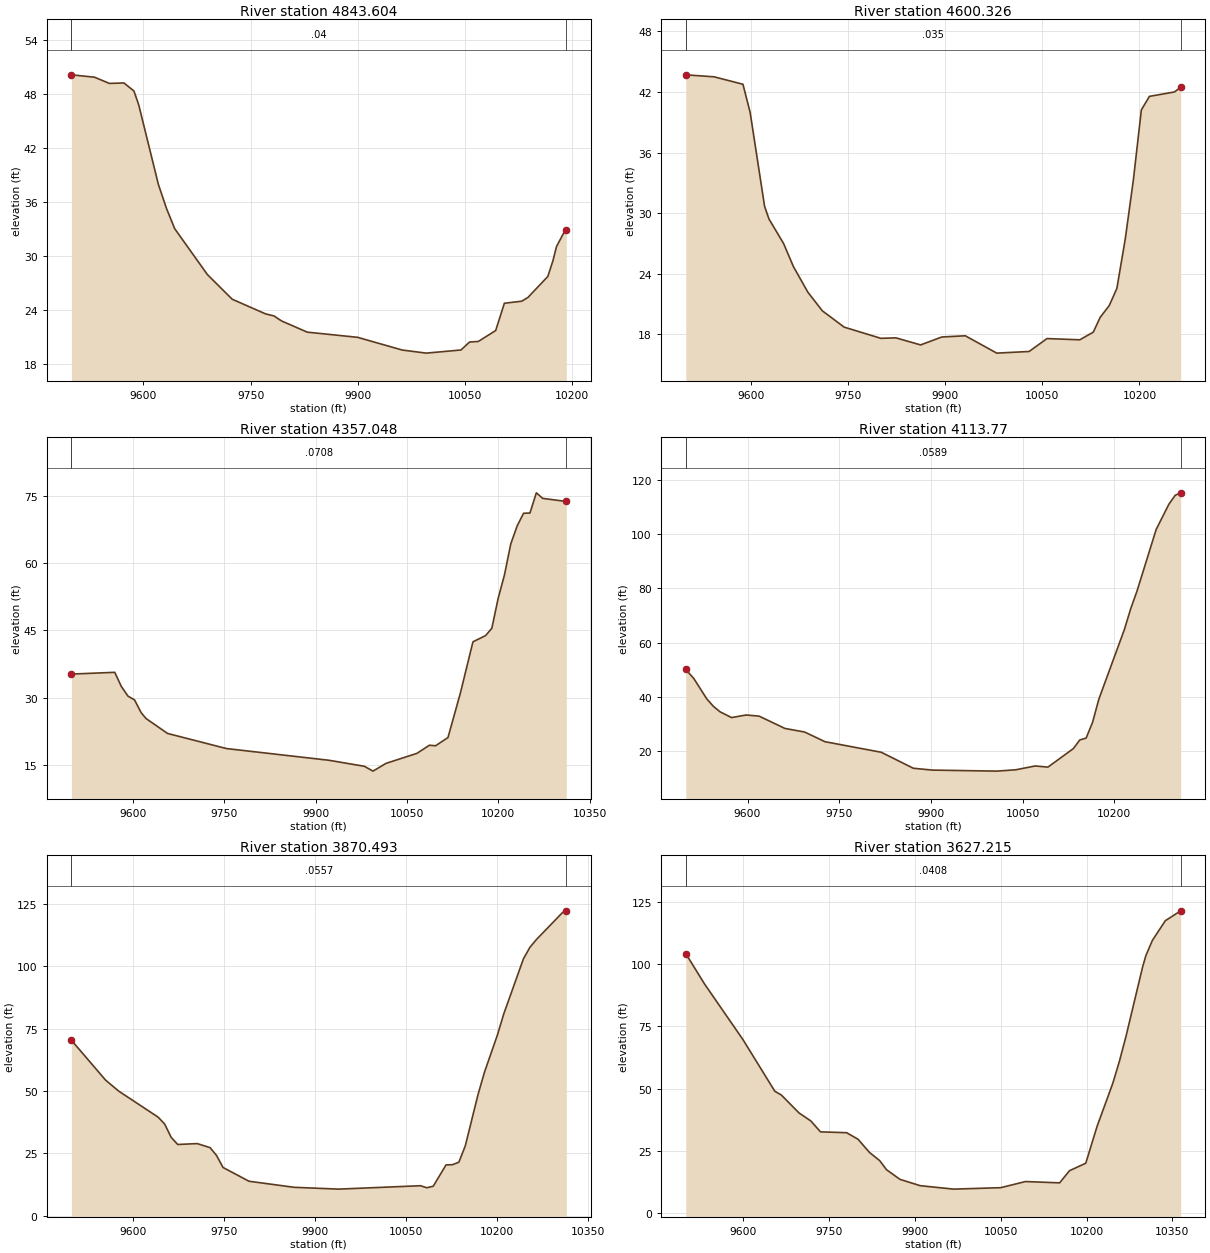
Type RM Length L Ch R = 1 ,4843.604,243.278000,243.278000,243.278000
XS GIS Cut Line= 6
377769.363829004849828.400709326377866.253832289850003.461991197
377961.518217161850161.190746959378014.741237368 850241.94538084
378025.490424862850257.498092618378135.628462136850416.303234063
#Sta/Elev= 30
9499.02850.106429531.31749.843339552.28849.151879572.61949.200819586.57648.31493
 9593.2746.788459620.86537.924389632.29435.241259643.72333.007889689.44127.91558
9724.27425.166319771.00423.539819782.68623.31388  9793.422.754789829.41621.50896
9899.91720.934439962.392 19.52119995.963  19.17810044.6419.5246810056.8120.41421
10068.9820.4743610093.3221.6887510105.4924.7211710129.8324.9479910138.51 25.3662
10166.3427.6966710173.6129.47015 10178.531.0179110190.67 32.834110192.2632.90183
#Mann= 3 , 0 , 0
9499.028    0.04       09499.028    0.04       010192.26    0.04       0
#XS Ineff= 2 , 0
       0                               0
Bank Sta=9499.028,10192.26
Exp/Cntr=0.3,0.1

Type RM Length L Ch R = 1 ,4600.326,243.277900,243.277900,243.277900
XS GIS Cut Line= 6
377578.267700462849955.724065593 377679.01623944850160.542231877
377750.347187881850286.691379014377833.219932816850406.786958158
377909.407224683850486.793190561 377990.27384313850594.748343157
#Sta/Elev= 30
 9499.0543.69554 9542.8243.498449587.397 42.76119598.54239.96605 9620.8330.66762
9627.58229.420529650.23826.984989665.40824.701469687.69622.168319709.98520.32823
9743.74218.709269800.58517.598489823.58917.648529861.90216.947229894.49817.73153
 9930.9317.852929979.50716.1345610029.5216.2983610057.1417.5763910107.7717.45437
10128.6618.2126210139.2519.6716710153.3220.8478510165.0622.5360510177.9727.40544
10190.4633.22176 10202.940.2208610215.3441.5618510254.1341.9992110263.6442.46716
#Mann= 3 , 0 , 0
 9499.05   0.035       0 9499.05   0.035       010263.64   0.035       0
#XS Ineff= 2 , 0
       0                               0
Bank Sta=9499.05,10263.64
Exp/Cntr=0.3,0.1

Type RM Length L Ch R = 1 ,4357.048,243.277900,243.277900,243.277900
XS GIS Cut Line= 6
377477.835169899850029.320726903377600.825393271850336.680155361
377652.509068608850520.944470174 377673.34735671850633.806023265
377693.230008612850710.368047367377723.624679675850801.498137677
#Sta/Elev= 30
9499.06435.265379570.22835.661619581.06332.511839591.89930.362499602.734 29.5115
9613.56926.683569621.575 25.37099656.90922.045889753.70118.678459921.93316.07229
9980.11314.72774 9994.2613.6529610015.4615.3680510066.5417.6191810086.8819.41883
10097.0519.3058210117.38 21.132810137.7431.03912 10158.442.4586310179.0743.83272
 10189.445.4731910199.7352.1062210210.0657.3151310220.4864.2568510230.9868.27467
10241.4971.0848310251.9971.13984 10262.575.6411610273.01 74.399610311.6973.71787
#Mann= 3 , 0 , 0
9499.064  0.0708       09499.064  0.0708       010311.69  0.0708       0
#XS Ineff= 2 , 0
       0                               0
Bank Sta=9499.064,10311.69
Exp/Cntr=0.3,0.1

Type RM Length L Ch R = 1 , 4113.77,243.277900,243.277900,243.277900
XS GIS Cut Line= 6
377248.207959253850062.831300241377284.936620504850158.748850758
377325.906704547 850276.77682036377382.528667389 850461.66561849
377431.200479788850614.024070628377494.989951541850833.419273059
#Sta/Elev= 30
9499.01750.066739512.04746.781139533.46439.195859544.17236.46954 9554.8834.47437
9573.93932.312749597.712 33.26619618.92932.84976 9661.2728.298699693.40326.98218
9726.66323.41382 9818.9319.494759871.22313.597469902.59812.9226510007.5212.54336
10039.0113.04676 10070.514.44587 10091.4 14.028110133.0320.8773210143.4424.04937
10153.8524.7377210164.2630.4883210174.6639.12271 10216.364.7502910226.71 72.4719
10237.1179.0616710268.34 101.73510289.16 111.07510299.58114.390610308.46115.2914
#Mann= 3 , 0 , 0
9499.017  0.0589       09499.017  0.0589       010308.46  0.0589       0
#XS Ineff= 2 , 0
       0                               0
Bank Sta=9499.017,10308.46
Exp/Cntr=0.3,0.1

Type RM Length L Ch R = 1 ,3870.493,243.277900,243.277900,243.277900
XS GIS Cut Line= 6
 377003.54380221850122.997582132377069.385611312850284.200757714
377124.386418234 850432.85819276377193.877221362850671.160397381
377234.179636144850790.380378405377273.641043912850890.743642423
#Sta/Elev= 30
9499.03470.376849555.20654.40083 9576.8149.982269641.62239.546399652.424 36.7992
9663.22631.441029674.017 28.54919706.00428.914419727.32927.284719737.99224.12433
9748.654 19.32319791.30413.810859865.42111.376649938.85710.6430310073.5712.01035
10084.0111.1958510094.5711.8030810115.6820.3648510126.2420.4430110136.7921.44016
10147.3527.9908410168.4648.7055510179.0257.6131510200.1372.4061410210.7781.00049
10243.01103.007510253.75107.6666 10264.5110.800410307.48121.638310313.65122.3012
#Mann= 3 , 0 , 0
9499.034  0.0557       09499.034  0.0557       010313.65  0.0557       0
#XS Ineff= 2 , 0
       0                               0
Bank Sta=9499.034,10313.65
Exp/Cntr=0.3,0.1

Type RM Length L Ch R = 1 ,3627.215,243.278000,243.278000,243.278000
XS GIS Cut Line= 6
376704.773468282850265.782977708376851.003257161850543.366555858
376911.776068414850640.263777848376982.598368952850735.010859295
377050.688355106850839.473641451377146.457576468851008.663333599
#Sta/Elev= 30
9499.046 104.3179531.77892.120649598.99769.759689654.81248.981569666.21647.45753
9697.13540.250749717.79637.038159734.71832.644329780.42932.304319800.44229.66859
9820.36724.382219838.38221.058159850.18617.435219873.79413.544539909.20611.00887
9967.6059.62780910049.95 10.207710093.2912.6785910152.9712.1420510170.2517.03308
 10198.720.0409210218.5834.9234910246.07 52.219210257.6461.1011810269.2171.16938
 10298.198.9038310303.85103.490310315.19109.581410337.86117.509210364.69121.4862
#Mann= 3 , 0 , 0
9499.046  0.0408       09499.046  0.0408       010364.69  0.0408       0
#XS Ineff= 2 , 0
       0                               0
Bank Sta=9499.046,10364.69
Exp/Cntr=0.3,0.1

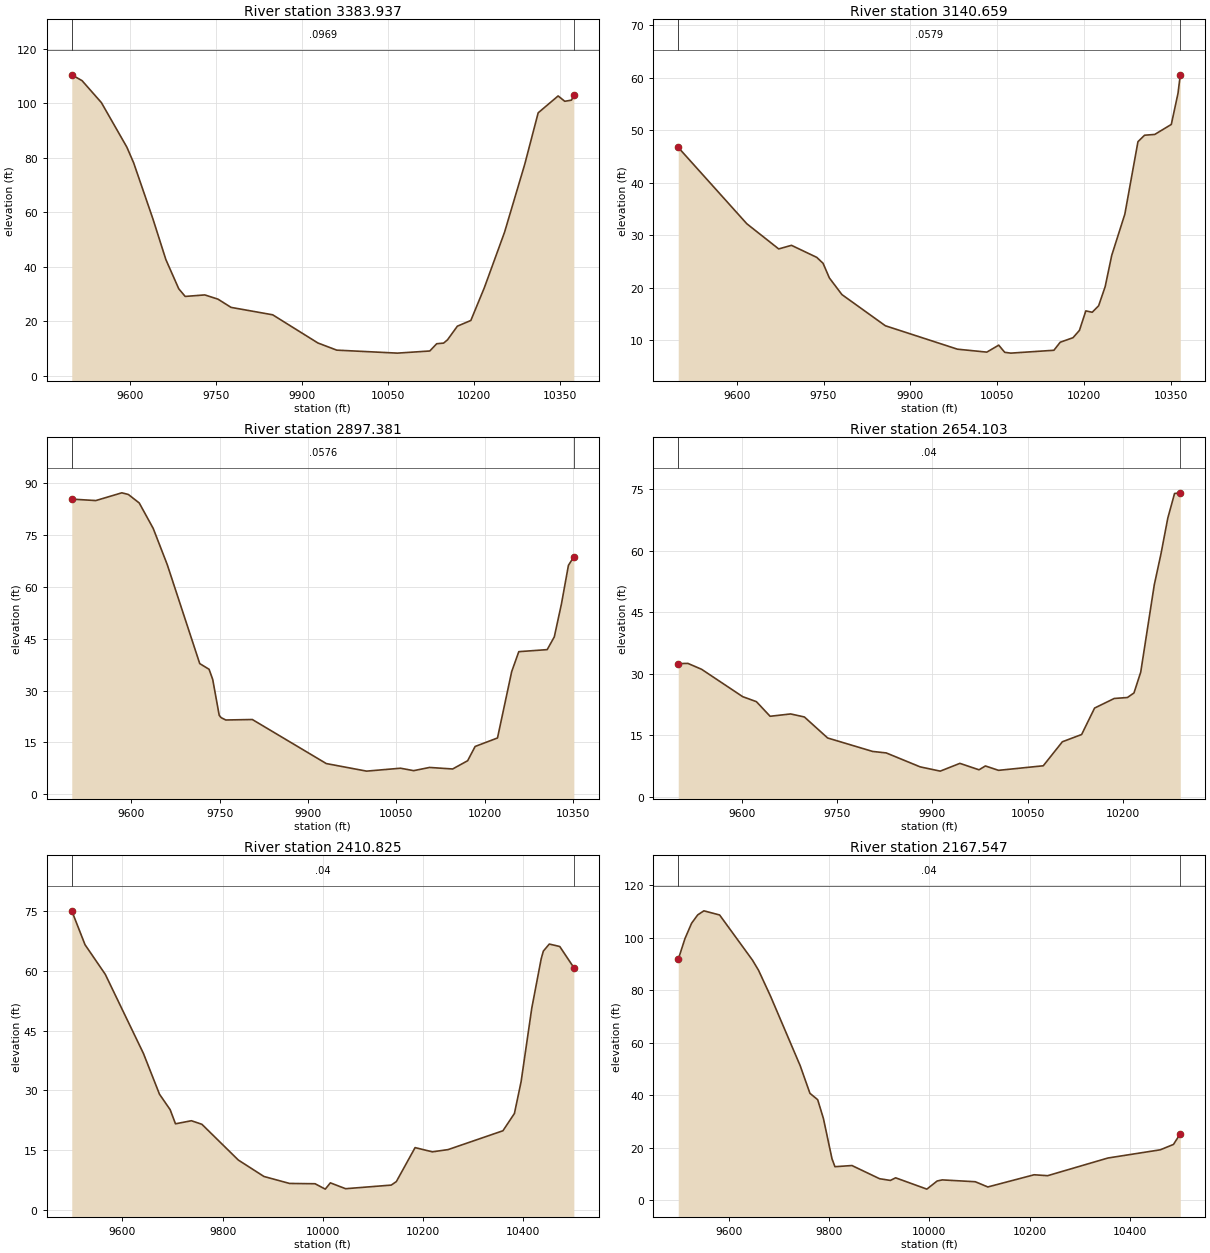
Type RM Length L Ch R = 1 ,3383.937,243.277900,243.277900,243.277900
XS GIS Cut Line= 6
376521.396673012 850419.03866026376616.043297938850604.491184141
376689.948750809850737.155963385376736.053060388850809.701402089
376864.349582607850994.734279518376969.405563571851168.636151789
#Sta/Elev= 30
9499.044110.46669516.964108.32949550.645100.26929594.96583.94229 9606.7878.20387
9640.46157.566049662.91542.692859685.36931.967999696.59629.156079730.72929.71621
9753.62328.164789776.51725.137359848.94522.421199927.65112.089399960.4659.455346
10066.268.35891410122.59 9.1430810134.5911.8034210146.5912.0345110153.3613.22325
10170.5918.2419710194.0720.3450910217.5532.3401310252.7852.7180710288.0177.69619
10311.3596.5306710346.09102.719910357.67100.757310369.25101.170610373.46102.8907
#Mann= 3 , 0 , 0
9499.044  0.0969       09499.044  0.0969       010373.46  0.0969       0
#XS Ineff= 2 , 0
       0                               0
Bank Sta=9499.044,10373.46
Exp/Cntr=0.3,0.1

Type RM Length L Ch R = 1 ,3140.659,243.277900,243.277900,243.277900
XS GIS Cut Line= 6
376365.503298899850477.645444934 376505.73348852 850794.12304268
376533.899561449850884.173056833376556.917911642851002.541501521
376588.843630956851091.471091098376687.095773141851278.455658389
#Sta/Elev= 30
9499.03146.705859617.42432.164779672.56527.364089694.62228.046929738.29825.75441
 9749.1924.623869760.08121.834099781.77218.661029856.78112.723059981.3498.258352
10032.03 7.6981710052.589.028408 10062.97.666507 10073.4 7.50855 10147.98.052321
10158.779.583458 10180.9 10.449410191.9611.8363910203.0215.5573210214.0815.29415
10225.1516.5388510236.4520.1839310247.7726.1396810270.4233.9947310293.0647.79446
10304.48 49.028910322.0349.1763610350.6751.0836210362.2257.0094310366.2160.53564
#Mann= 3 , 0 , 0
9499.031  0.0579       09499.031  0.0579       010366.21  0.0579       0
#XS Ineff= 2 , 0
       0                               0
Bank Sta=9499.031,10366.21
Exp/Cntr=0.3,0.1

Type RM Length L Ch R = 1 ,2897.381,243.277900,243.277900,243.277900
XS GIS Cut Line= 6
376086.708921058850607.964124554376193.614198719850837.936050731
 376251.20669019850942.233944462376332.729715668851052.497646113
376467.979824953851211.879324199376542.063766409851322.814153838
#Sta/Elev= 30
 9499.0485.300069539.88284.881379583.99287.11677 9595.0286.649999613.59884.18977
9637.32176.840139661.18666.373519716.32537.79251 9732.2136.14019 9738.3833.20815
9749.40822.841529752.64522.180999760.60321.501079805.66421.63736 9931.228.914104
 9999.616.730199 10057.37.571592 10079.66.86545110106.497.79292310145.797.351426
10171.249.73516110183.9613.8537910221.9216.3040810246.0435.48337 10258.1 41.2354
10306.3341.8273210318.3945.5133310330.44 54.956110342.3866.1697310351.57 68.6358
#Mann= 3 , 0 , 0
 9499.04  0.0576       0 9499.04  0.0576       010351.57  0.0576       0
#XS Ineff= 2 , 0
       0                               0
Bank Sta=9499.04,10351.57
Exp/Cntr=0.3,0.1

Type RM Length L Ch R = 1 ,2654.103,243.277900,243.277900,243.277900
XS GIS Cut Line= 6
376015.810434271850730.878770329376172.754311754851129.137200415
376177.115813512851170.102419256376163.738880318851258.600543836
376167.856293675851312.773679255376217.416416652 851483.51241892
#Sta/Elev= 30
9499.10532.475829514.363  32.5279535.97431.088749600.80624.401879622.417  23.181
9644.028  19.6149676.44420.184229698.05519.445839734.77114.31325 9805.6611.02933
9827.14610.664499880.7397.2561639912.3646.2185539943.3728.1150569973.5126.541978
9983.5837.47874810004.286.41065810074.867.52364310104.9913.3894510135.3815.16112
10155.8121.6219110186.8823.9658710207.5924.1961610217.9425.3118410228.5930.39907
10249.9351.68931 10260.659.3389210271.2767.9953610281.9474.0197210291.02 74.1863
#Mann= 3 , 0 , 0
9499.105    0.04       09499.105    0.04       010291.02    0.04       0
#XS Ineff= 2 , 0
       0                               0
Bank Sta=9499.105,10291.02
Exp/Cntr=0.3,0.1

Type RM Length L Ch R = 1 ,2410.825,243.278000,243.278000,243.278000
XS GIS Cut Line= 6
375783.892147217850704.298745264375842.275212093850836.030553254
375889.665472099850974.009962459375982.736023109 851423.79468497
376029.122971783851528.938792821376100.258328642851646.084350747
#Sta/Elev= 30
9499.02975.156949525.475 66.64099565.91759.187299642.02339.300049674.02529.05748
9695.34725.155439706.00821.602279737.76122.368489758.70421.479759831.44312.48128
9882.6488.3468179933.6516.6003759984.5486.526942 10004.9 5.1731210015.086.752159
10045.495.27831210136.576.18680510146.757.07251610184.14 15.611910218.7114.54856
10250.1315.1176110359.4719.8524710382.3824.1967710395.69 32.181110416.9950.67497
10435.7963.0891310440.0965.02916   1045266.8025710472.87 66.182210500.9560.87136
#Mann= 3 , 0 , 0
9499.029    0.04       09499.029    0.04       010500.95    0.04       0
#XS Ineff= 2 , 0
       0                               0
Bank Sta=9499.029,10500.95
Exp/Cntr=0.3,0.1

Type RM Length L Ch R = 1 ,2167.547,243.277900,243.277900,243.277900
XS GIS Cut Line= 6
375457.214311115850793.278999067375637.566609893851072.236957966
375674.610573131 851153.72751012375705.454731344851270.079898396
375725.316489873  851311.8160324375993.781779384851625.528309622
#Sta/Elev= 30
9499.055 91.7276 9512.5199.677559525.687105.50469537.949108.7009 9550.21110.2438
9581.636108.65939647.29791.426979659.33587.574989683.41377.635919742.41351.21894
9761.84540.711369777.31938.272069788.78631.088449805.80515.809149811.71912.74656
9845.697 13.18699900.7738.1672679922.3797.5113159932.8718.5052179995.1534.197556
 10015.77.29122810025.997.713752 10091.87.01291310116.825.02245910209.199.667905
10236.099.31680610356.38 16.049910460.9819.1812610487.2621.2329610500.8925.30569
#Mann= 3 , 0 , 0
9499.055    0.04       09499.055    0.04       010500.89    0.04       0
#XS Ineff= 2 , 0
       0                               0
Bank Sta=9499.055,10500.89
Exp/Cntr=0.3,0.1

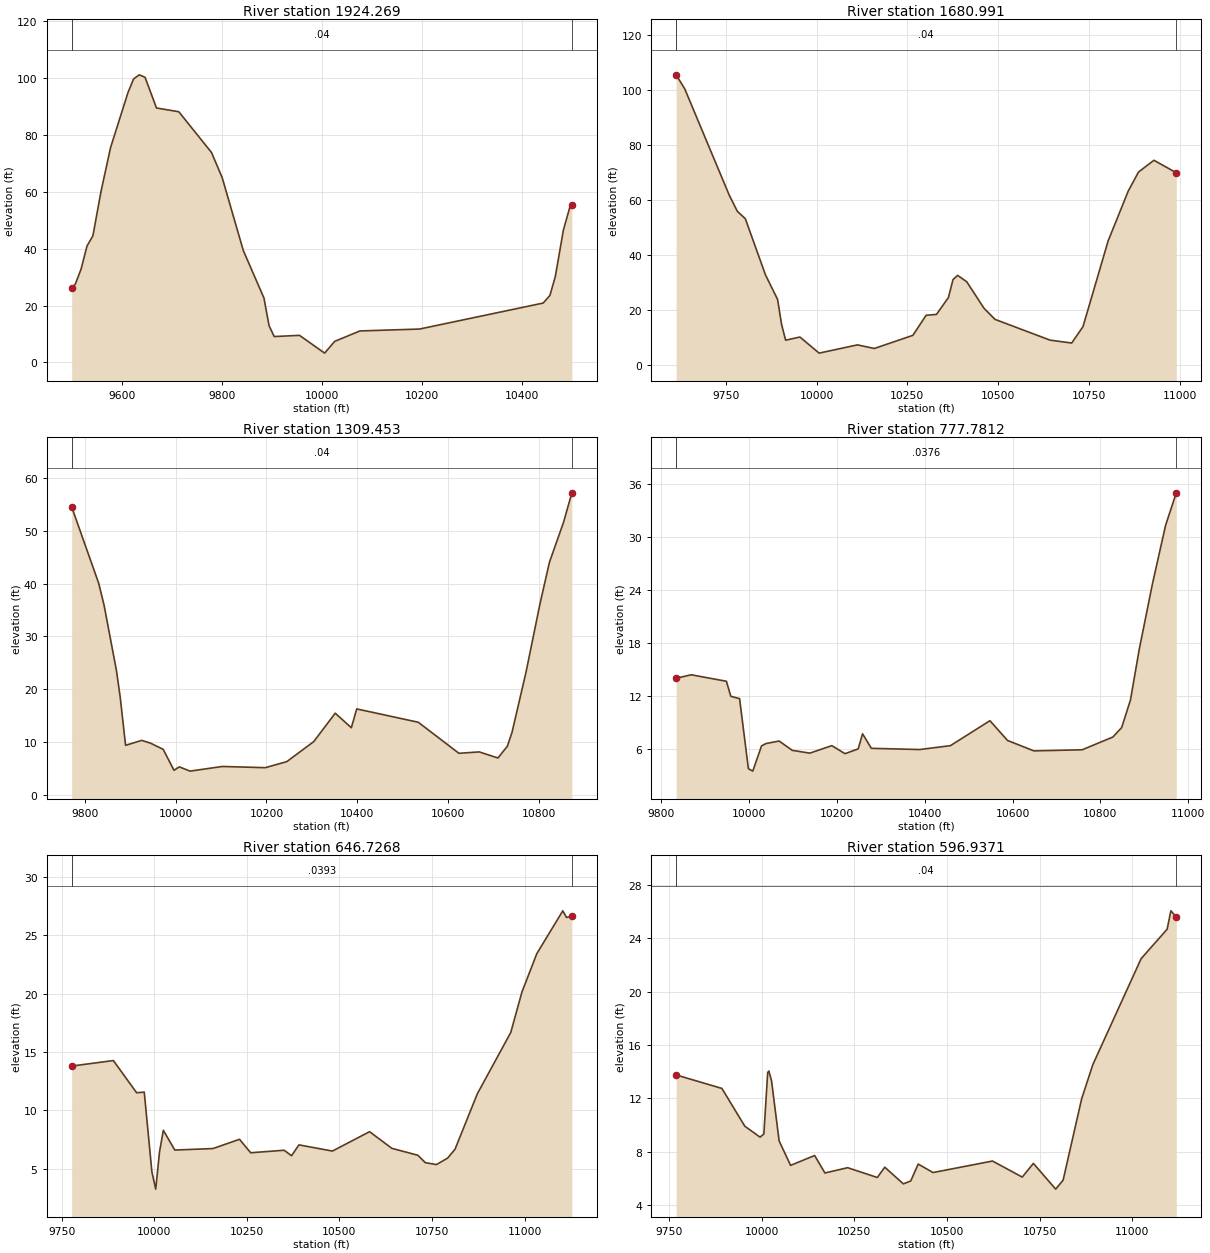
Type RM Length L Ch R = 1 ,1924.269,243.277900,243.277900,243.277900
XS GIS Cut Line= 6
375139.067956259851233.550464132375414.106007638851377.899960338
375686.294097307851428.133153086375763.293272628 851456.88482178
375868.851801884851533.262440009376007.308631697851677.569663163
#Sta/Elev= 30
9499.07726.273369506.09127.416569517.91532.816059529.73840.938999541.56244.52237
 9558.0260.313169577.03375.626089611.735 94.89179623.177 99.7778 9634.62 101.187
9646.062100.29959668.94789.515349713.60788.198759779.18773.83708 9800.6564.92984
9842.722 39.39429884.17222.630919894.412 12.90849904.6539.0840729955.3419.507375
10005.653.25150110025.787.38797110076.3811.0552310195.7611.7247910443.3320.87103
10456.8423.5501310467.64 30.191610483.8546.5755110497.3655.0162710500.8355.28621
#Mann= 3 , 0 , 0
9499.077    0.04       09499.077    0.04       010500.83    0.04       0
#XS Ineff= 2 , 0
       0                               0
Bank Sta=9499.077,10500.83
Exp/Cntr=0.3,0.1

Type RM Length L Ch R = 1 ,1680.991,371.538600,371.538600,371.538600
XS GIS Cut Line= 6
375204.022101283851474.729266835375497.412616666851617.765182257
375782.047285236 851792.18271258375986.252432931851950.555267263
376116.465561265 852068.66559001376318.611721872852266.008293964
#Sta/Elev= 30
9613.231105.43589637.004100.35919759.57161.700549781.74955.842799803.92753.12017
9859.37232.71508 9892.6423.804769903.72914.696829914.8188.9708439954.15810.12111
   100074.26611210112.567.26067810159.115.95565110265.1610.7310310301.7118.02786
 10330.218.3415510363.05 24.474510375.7131.0093110388.3932.5312610413.4530.22191
10461.2720.5299310491.3216.5403910642.93  8.985910702.467.93900410733.5913.89986
10802.8445.0774710858.2863.2174310886.5170.1083110928.8774.3690610990.4469.84042
#Mann= 3 , 0 , 0
9613.231    0.04       09613.231    0.04       010990.44    0.04       0
#XS Ineff= 2 , 0
       09940.228        10349.54       0
Bank Sta=9613.231,10990.44
Exp/Cntr=0.3,0.1

Type RM Length L Ch R = 1 ,1309.453,531.671500,531.671500,531.671500
XS GIS Cut Line= 3
375144.720829337851832.429421415375683.949557059852172.818228253
376132.753330144852285.513987496
#Sta/Elev= 30
9771.47654.544839830.93540.05533 9842.7635.89901 9869.9623.513099878.23718.48899
9890.063  9.3315 9925.5410.273649944.8969.7452799972.8438.5713329996.4954.606116
10008.325.24885210031.974.44295210102.935.32461210197.535.09718510244.836.247866
10303.96 10.036110351.2715.4233710386.7412.6662210398.5716.2364210533.9613.70897
10623.417.822099   106688.08675210709.246.93379910729.869.15752510740.1711.78113
 10771.123.2482910802.0336.2948810822.6544.0772310853.5951.6311110871.8957.20492
#Mann= 3 , 0 , 0
9771.476    0.04       09771.476    0.04       010871.89    0.04       0
#XS Ineff= 2 , 0
       09928.805        10321.92       0
Bank Sta=9771.476,10871.89
Exp/Cntr=0.3,0.1

Type RM Length L Ch R = 1 ,777.7812,131.054400,131.054400,131.054400
XS GIS Cut Line= 3
 374920.39973466 852406.51713838375818.837234656852430.388666171
376059.350161358852435.582926885
#Sta/Elev= 30
9833.57313.984879868.18614.377399948.21413.639989958.21711.933229978.22511.67051
9998.2323.71666610008.243.43819310028.246.30726910038.256.56627710068.266.857002
10098.275.79520710138.285.481901 10188.36.33230110218.315.41926710248.325.961466
10258.327.67495810278.336.02666410388.375.88995210458.39 6.3291610548.439.164769
10588.446.92343710648.465.736456 10758.55.86115210828.517.31112810848.528.386063
10868.5211.5198610888.53 17.269310918.5324.6943510948.5431.34741 10972.935.03807
#Mann= 3 , 0 , 0
9833.573  0.0376       09833.573  0.0376       0 10972.9  0.0376       0
#XS Ineff= 2 , 0
       0                10296.48       0
Bank Sta=9833.573,10972.9
Exp/Cntr=0.3,0.1

Type RM Length L Ch R = 1 ,646.7268,49.789700,49.789700,49.789700
XS GIS Cut Line= 3
374874.826818005852487.680332807375300.174040216852594.017138348
376209.462234682852518.062277247
#Sta/Elev= 30
9777.01313.797219889.65514.268799952.42311.510089973.03911.565249993.6544.731423
10003.963.24999610014.276.43621710024.588.290798 10055.56.59943510158.586.726822
10230.337.51993110260.436.36647110350.756.58165510370.82 6.1129710390.89 7.04288
 10481.26.51177410581.558.17283510641.766.745208   107126.15236810732.075.518342
10762.175.35477610792.285.90784910812.356.67235210872.56 11.418410962.8716.67707
10992.98 20.137711033.1123.4246711103.3627.1010411113.3926.5352111127.9126.62821
#Mann= 3 , 0 , 0
9777.013  0.0393       09777.013  0.0393       011127.91  0.0393       0
#XS Ineff= 2 , 0
       0                10254.46       0
Bank Sta=9777.013,11127.91
Exp/Cntr=0.3,0.1

Type RM Length L Ch R = 1 ,596.9371,25.078400,25.078400,25.078400
XS GIS Cut Line= 3
374864.979233299852534.249786548375290.326204536852640.586477385
376199.613827043852564.631556543
#Sta/Elev= 30
9768.48213.746789892.19712.735619954.0439.9040349995.2759.08102110005.589.316775
10015.8913.9299910018.96 14.0357 10026.213.3197410046.818.79675610077.746.965191
10142.667.70464610170.516.39410410231.686.79107910311.966.05651810332.036.828277
 10382.25.57971410402.275.79739910422.347.06326610462.486.42671310623.047.291466
10703.326.08616210733.427.11309110793.635.184149 10813.75.85724310863.87 11.9645
10893.9814.5187711024.4322.4646511094.6724.6730111104.7126.0510811119.3725.58855
#Mann= 3 , 0 , 0
9768.482    0.04       09768.482    0.04       011119.37    0.04       0
#XS Ineff= 2 , 0
       0                10247.31       0
Bank Sta=9768.482,11119.37
Exp/Cntr=0.3,0.1

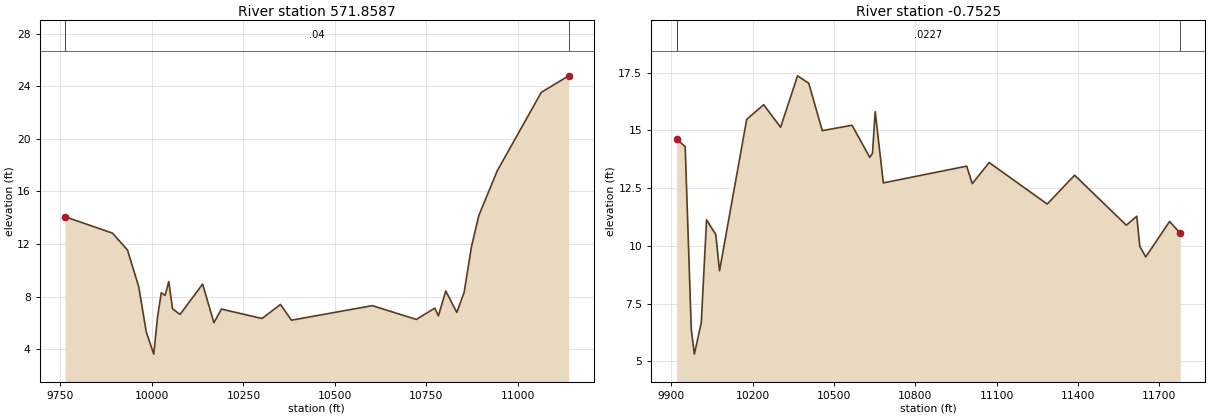
Type RM Length L Ch R = 1 ,571.8587,572.611200,572.611200,572.611200
XS GIS Cut Line= 3
374848.785151333852559.294916092375293.663623572852663.461582811
376209.462234677852583.166443956
#Sta/Elev= 30
9762.45814.074849892.08712.831779933.16911.54669 9963.988.7553979984.5215.316237
10005.063.62482210015.336.434551 10025.68.29460310035.87 8.0901210046.149.139487
10056.417.06904810076.966.64472210138.588.95487910169.396.01592910189.937.049859
10301.02 6.3347210351.217.40359810381.326.20612110602.177.31271310722.636.261156
10772.827.12427110782.866.53473710802.948.42766610833.056.79701110853.138.318826
 10873.211.8063210893.2814.1677210943.4717.5614311063.9323.5342511138.6824.79354
#Mann= 3 , 0 , 0
9762.458    0.04       09762.458    0.04       011138.68    0.04       0
#XS Ineff= 2 , 0
       0                10252.14       0
Bank Sta=9762.458,11138.68
Exp/Cntr=0.3,0.1

Type RM Length L Ch R = 1 , -0.7525,0.000000,0.000000,0.000000
XS GIS Cut Line= 6
374623.036453422852926.807936988374723.730897861853078.500645282
375169.694439536853202.198561976375374.772564533853197.858284197
 375993.26214786853333.491964774376330.718745098853487.571825848
#Sta/Elev= 30
 9919.6114.624479951.369  14.2919973.8996.3752789985.1645.30847210010.756.666576
10030.2211.1237610064.2810.4823410078.078.916682 10178.2 15.470610240.7516.10636
10303.2915.1317310365.8317.3570910407.1217.0382510456.9414.9841610566.78  15.217
10632.1113.8243410642.1114.0067510652.1115.8071510682.1212.7207210989.4813.44702
11010.1712.6872211072.2713.6032411286.4911.8054611387.5913.0535611578.2210.89112
11616.8311.2766311627.839.97649911649.819.51689111737.7611.0502311777.0210.54744
#Mann= 3 , 0 , 0
 9919.61  0.0227       0 9919.61  0.0227       011777.02  0.0227       0
#XS Ineff= 2 , 0
       0                10733.12       0
Bank Sta=9919.61,11777.02
Exp/Cntr=0.3,0.1